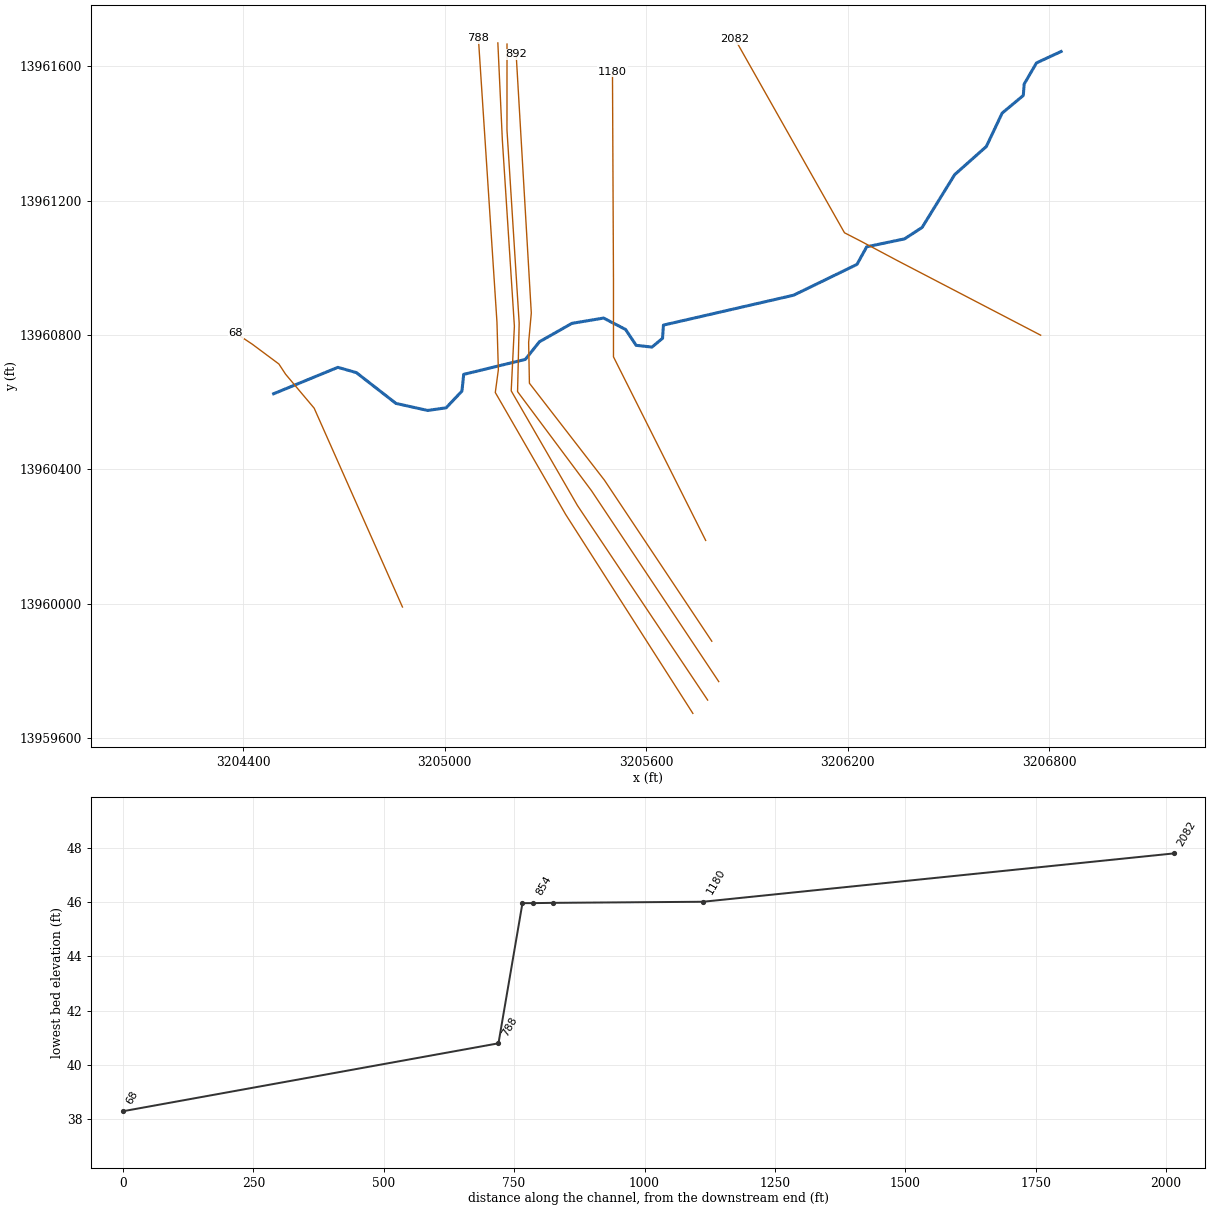
--- S114-00-00.prj (project) ---

Proj Title=S114-00-00
Current Plan=p05
Default Exp/Contr=.3,.1
English Units
Geom File=g01
Flow File=f05
Flow File=f06
Plan File=p04
Plan File=p05
Y Axis Title=Elevation
X Axis Title(PF)=Main Channel Distance
X Axis Title(XS)=Station
BEGIN DESCRIPTION:
Luce Bayou Watershed
Mexican Gully
HCFCD unit S114-00-00
(Flood Hazard, Floodway)Model
10, 2, 1, 0.2% Event
Filename S1140000.prj
Prepared by:  FTN Associates Ltd.   DATE:  February 2003
Reviewed by: 	 DATE:
STATUS (Final)
Critical Depth Slope was calulated to be 0.0035 using the two most downstream River Stations - RS 68 and RS 788
Manning's "n" values were determined from HEC-2 data (June 1980)
END DESCRIPTION:
DSS Export Rating Curves= 0
DSS Export Rating Curve Sorted= 0
DSS Export Volume Flow Curves= 0
DXF OffsetX= 0
DXF OffsetY= 0
DXF ScaleX= 1
DXF ScaleY= 10

--- S114-00-00.p05 (plan) ---

Plan Title=Floodway
Version=Version 3.0.1  Mar 2001
Short Identifier=Floodway0607
Geom File=g01
Flow File=f05
Subcritical Flow
K Sum by GR= 0
Std Step Tol= 0.01
Critical Tol= 0.01
Num of Std Step Trials= 20
Max Error Tol= 0.3
Flow Tol Ratio= 0.001
Split Flow NTrial= 30
Split Flow Tol= 0.02
Split Flow Ratio= 0.02
Log Output Level= 0
Friction Slope Method= 1
Unsteady Friction Slope Method= 2
Parabolic Critical Depth
Global Vel Dist= 0 , 0 , 0
Global Log Level= 0
CheckData=True
Encroach Param=-1 ,0,0, 2
Encroach River=S114-00-00
Encroach Reach=Mexican Gully
Encroach Node=2082
       1     536     637
Encroach Node=1180
       1   669.3     754
Encroach Node=892
       1  968.83 1057.81
Encroach Node=854
       1    1095    1208
Encroach Node=844
       1    1095    1208
Encroach Node=834
       1 1099.57 1204.16
Encroach Node=788
       1    1180    1216
Encroach Node=68
       1     671   796.1
Encroach Reach=S114-00-00_0001
Encroach Node=2082
       1     536     637
Encroach Node=1180
       1   669.3     754
Encroach Node=892
       1  968.83 1057.81
Encroach Node=854
       1    1095    1208
Encroach Node=844
       1    1095    1208
Encroach Node=834
       1 1099.57 1204.16
Encroach Node=788
       1    1180    1216
Encroach Node=68
       1     671   796.1
Computation Interval=1HOUR
Output Interval=1HOUR
Run HTab= 0
Run UNet= 0
Run PostProcess= 0
UNET Theta= 1
UNET ZTol= 0.02
UNET ZSATol= 0.1
UNET MxIter= 20
UNET MaxInSteps= 20
UNET DtIC= 0
UNET DtMin= 0
UNET MaxCRTS= 20
UNET WFStab= 2
UNET SFStab= 1
UNET WFX= 1
UNET SFX= 1
UNET Convert EG Bridges=-1
UNET Use Existing IB Tables=-1
Instantaneous Interval=1HOUR
Write IC File= 0
Write Velocity= 0
Write Detailed= 0

--- S114-00-00.p04 (plan) ---

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Plan Title=FEMA Effective June 2007
Short Identifier=FEMAeff0607
Geom File=g01
Flow File=f06
IC Time=0

--- S114-00-00.f05 (steady flow) ---

Flow Title=Floodway
Version=Version 3.0.1  Mar 2001
Number of Profiles= 2
Profile Names=1PCT_100yr,1PCTFloodway_100yrFW
River Rch & RM=S114-00-00,S114-00-00_0001 ,2082
     555     555
River Rch & RM=S114-00-00,S114-00-00_0001 ,1180
     572     572
River Rch & RM=S114-00-00,S114-00-00_0001 ,892
     578     578
River Rch & RM=S114-00-00,S114-00-00_0001 ,788
     623     623
Boundary for River Rch & Prof#=S114-00-00,S114-00-00_0001 , 1
Up Type= 0
Dn Type= 3
Dn Slope=.0035
DSS Import GetInterval= 0
DSS Import GetPeak= 0
DSS Import FillOption= 0

--- S114-00-00.f06 (steady flow) ---

Flow Title=FEMA Effective June 2007
Version=Version 3.0.1  Mar 2001
Number of Profiles= 4
Profile Names=10PCT_10yr,2PCT_50yr,1PCT_100yr,0.2PCT_500yr
River Rch & RM=S114-00-00,S114-00-00_0001 ,2082
     323     477     555     777
River Rch & RM=S114-00-00,S114-00-00_0001 ,1180
     333     492     572     800
River Rch & RM=S114-00-00,S114-00-00_0001 ,892
     336     497     578     809
River Rch & RM=S114-00-00,S114-00-00_0001 ,788
     362     535     623     872
Boundary for River Rch & Prof#=S114-00-00,S114-00-00_0001 , 1
Up Type= 0
Dn Type= 3
Dn Slope=.0035
DSS Import GetInterval= 0
DSS Import GetPeak= 0
DSS Import FillOption= 0

--- S114-00-00.g01 (geometry) ---

Geom Title=S114-00-00 June 2007
Version=Version 3.0.1  Mar 2001

River Reach=S114-00-00      ,S114-00-00_0001
Reach XY= 30
      3206834.84    13961643.606     3206761.517    13961609.563
     3206724.855    13961546.715     3206722.237    13961512.672
     3206659.388    13961460.298     3206612.252    13961360.788
     3206517.979     13961276.99     3206421.088    13961119.869
     3206368.714    13961085.826     3206256.111    13961062.258
     3206227.305    13961009.884      3206038.76     13960918.23
     3205651.195    13960829.195     3205648.576    13960789.915
     3205617.152    13960763.728     3205570.015    13960768.965
     3205538.591    13960816.101     3205473.124    13960850.144
     3205378.851    13960834.432      3205281.96     13960779.44
     3205240.061    13960727.066     3205065.569     13960684.69
     3205056.753    13960682.548     3205051.516    13960632.793
     3205004.379    13960583.038     3204949.387    13960575.182
     3204855.114    13960596.132     3204737.274    13960687.786
     3204682.281    13960703.498     3204491.117    13960624.937

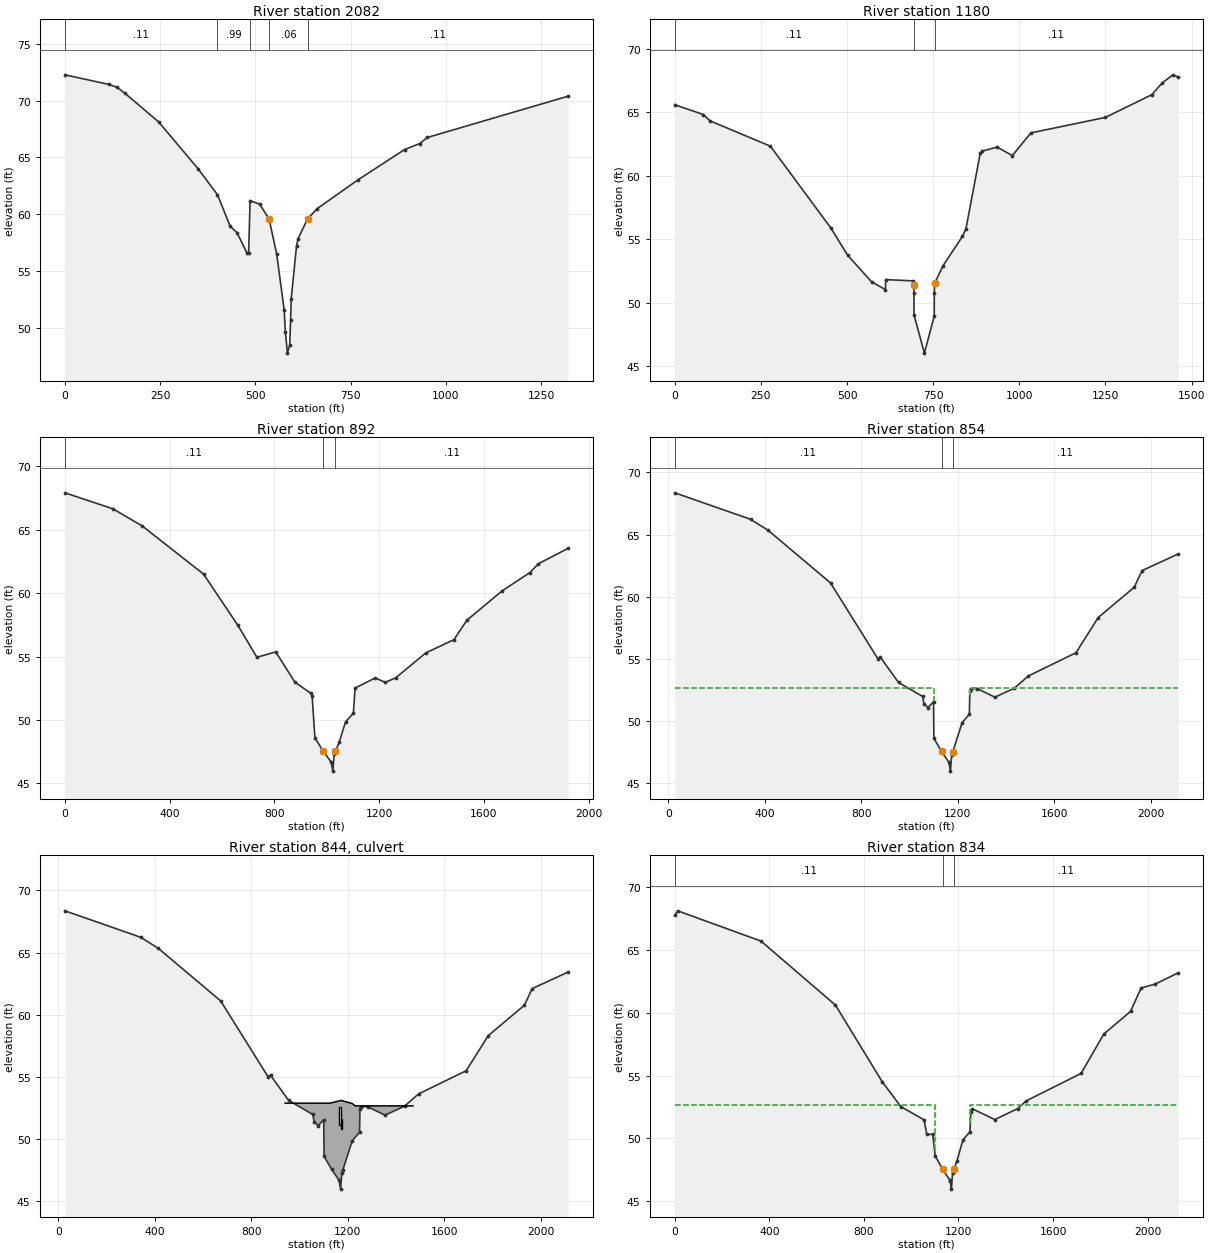
Type RM Length L Ch R = 1 ,2082    ,269,903,257
BEGIN DESCRIPTION:
482v1 set blocked flow stationing @ 486.14 and 690.61
rounded off bank stations and reach lengths
Channel reach length is longer than the ROB and LOB
END DESCRIPTION:
XS GIS Cut Line= 6
      3206773.93    13960799.157     3206346.143    13961021.851
     3206282.991     13961055.49       3206237.6     13961079.53
     3206190.035    13961104.014     3205864.099    13961680.577
#Sta/Elev= 30
       0   72.26  116.03   71.41  137.22   71.16  157.79   70.63  246.04   68.12
  349.11   64.02  400.51   61.72  433.75   58.94  451.75   58.39  478.34   56.56
  482.28   56.55  486.14   61.19  511.14   60.89     536   59.59     556   56.49
  575.64   51.59  578.74   49.69  584.14   47.79  590.14   48.49  592.54   50.69
  594.14   52.59     608   57.19  612.14   57.86     637   59.59  662.14   60.49
   770.5   63.05  891.86   65.69  931.06   66.21  951.52   66.75 1321.01   70.38
#Mann= 5 ,-1 , 0
       0     .11       0  400.51     .99       0  486.14     .11       0
     536     .06       0     637     .11       0
Bank Sta=536,637
XS Rating Curve= 0
Exp/Cntr=.3,.1

Type RM Length L Ch R = 1 ,1180    ,269,288,257
BEGIN DESCRIPTION:
482v2    rounded off reach lengths and bank stations
END DESCRIPTION:
XS GIS Cut Line= 6
     3205776.877    13960188.411     3205502.482    13960734.826
     3205502.482    13960814.306     3205502.482    13960875.722
     3205502.482    13960967.168     3205499.534    13961583.517
#Sta/Elev= 30
       0    65.6   82.78   64.83   102.1   64.33  277.58   62.33   453.2   55.87
  501.72   53.73  571.27   51.63  611.44   51.02  611.97   51.81  690.57   51.71
     694   51.41  694.07   50.76  694.37   49.01  724.47   46.01  752.97   48.91
  753.17   50.76     754   51.51  778.67   52.91  834.67   55.21  844.97   55.81
  886.56   61.78  891.81   61.94  935.54   62.26   979.6   61.59 1033.55   63.38
 1249.56    64.6  1384.2   66.39 1414.73   67.32 1445.55   67.96 1460.14    67.8
#Mann= 3 , 0 , 0
       0     .11       0     694     .06       0     754     .11       0
Bank Sta=694,754
XS Rating Curve= 0
Exp/Cntr=.3,.1

Type RM Length L Ch R = 1 ,892     ,39,38,35
BEGIN DESCRIPTION:
copy 482s1d (4/4 Golf Cart crossing) Lake Houston GC Hole #17
(adj. invert in channel area as needed)
adjusted contraction/expansion coefficients
rounded off bank stations and reach lengths
LOB and ROB reach lengths are longer than the channel reach length
CHANGED LOB AND ROB TO EQUAL CHANNEL REACH LENGTH
END DESCRIPTION:
XS GIS Cut Line= 6
     3205795.142     13959888.38     3205475.565    13960367.745
     3205252.311    13960656.235     3205250.011    13960777.601
     3205257.943    13960865.108     3205212.891    13961635.001
#Sta/Elev= 30
       0   67.92  183.01   66.66  295.06   65.31  529.36   61.51  660.36   57.47
  733.09   54.95   805.1   55.37   878.4   52.98  937.99   52.13     944   51.93
  954.65    48.6  986.37   47.54  1016.8   46.68 1023.21   45.97 1028.16   47.29
    1033   47.53 1047.22   48.23 1071.63   49.86 1101.65   50.54    1108   52.52
 1184.97   53.32 1223.56   52.97 1263.96   53.34 1377.77   55.29 1485.88   56.34
 1535.03   57.87 1669.05   60.18 1775.79   61.63 1808.51   62.33 1921.43   63.54
#Mann= 3 , 0 , 0
       0     .11       0  986.37     .06       0    1033     .11       0
Bank Sta=986.37,1033
XS Rating Curve= 0
Exp/Cntr=.5,.3

Type RM Length L Ch R = 1 ,854     ,23,20,19
BEGIN DESCRIPTION:
copy 482s1d (3/4 Golf Cart crossing) Lake Houston GC Hole #17
(adj. invert in channel area as needed)
adjusted contraction/expansion coefficents
Set ineffective flow areas @ stations 1141 and 1153
Adjusted elevations @ stations 1226.71, 1239.37, and 1524.7 to put the existing land below the bridge surface.
rounded off bank stations and reach lengths
END DESCRIPTION:
XS GIS Cut Line= 6
      3205815.78     13959768.24     3205437.247     13960336.04
     3205217.085    13960631.194     3205221.828    13960835.133
     3205185.542     13961409.99     3205185.641    13961665.657
#Sta/Elev= 30
   26.84   68.36  340.84   66.23  413.52   65.35  672.63   61.11  868.57   55.02
  879.31   55.13  954.57    53.1 1054.57   51.97 1060.72   51.33 1077.47   51.08
 1099.84   51.54 1101.47    48.6 1133.17   47.54 1163.62   46.67 1170.03   45.96
 1174.98   47.28 1179.84   47.53 1218.45   49.86 1248.47   50.54 1250.34   52.42
 1253.84    52.6 1281.54    52.6 1354.38   51.91 1435.25   52.64 1493.17   53.62
 1690.67   55.49 1782.62   58.32 1932.11   60.76 1964.56    62.1 2113.21   63.43
#Mann= 3 , 0 , 0
   26.84     .11       0 1133.17     .06       0 1179.84     .11       0
#XS Ineff= 2 , 0
       0    1100   52.66    1250       0   52.66
Permanent Ineff=
       F       F
Bank Sta=1133.17,1179.84
XS Rating Curve= 0
Exp/Cntr=.5,.3

Type RM Length L Ch R = 2 ,844     ,,,
BEGIN DESCRIPTION:
Golf Cart Path, at Lake Houston Golf Club Hole #17
Extended cart path dimensions horizontally to stations 940 and 1470.
NOTE:  This structure is an outlet for a golf course pond (water feature) thereby explaining the oddity of the outfall inverts.  Please refer to survey photos for further clarification.
END DESCRIPTION:
Bridge Culvert--1,0,-1,-1, 0
Deck Dist Width WeirC Skew NumUp NumDn MinLoCord MaxHiCord MaxSubmerge Is_Ogee
3.25,13.5,2.6,0, 6, 6, 52.66, , .95, 0, 0,0,,
     940 1125.96 1172.56 1218.34 1230.26    1470
   52.88   52.88    53.1   52.85   52.66   52.66
                                                
     940 1125.96 1172.56 1218.34 1230.26    1470
   52.88   52.88    53.1   52.85   52.66   52.66
                                                
BR Coef=-1 , 0 , 0 ,, 0 ,,,.8,-1,,0,
WSPro=,,,, 1 ,,,, 0 ,,,, 0 ,,,,-1 ,-1 ,-1 , 0 , 0 , 0 , 0 , 0
Culvert=2,1.5,5,13.5,.012,.5,1,10,1,51.11,1167.52,49.96,1167.52,LHGC #17 C#1, 0 ,3.25
Culvert Bottom n=.012
Culvert=2,.8,5,13.5,.012,.5,1,10,1,50.77,1173.34,50.75,1173.34,LHGC #17 C#2, 0 ,3.25
Culvert Bottom n=.012
BC Design=,, 0 ,, 0 ,,,,,,

Type RM Length L Ch R = 1 ,834     ,46,46,60
BEGIN DESCRIPTION:
copy 482s1d (2/4 Golf Cart crossing)  Lake Houston GC Hole #17
(adj. invert in channel area as needed)  adj. invert @ stations 1163.6, 1165.91, 1170.01, 1174.96, and 1175.98 to gain required DS invert
adjusted contraction/expansion coefficients
Set ineffective flow areas @ stations 1201 and 1212
rounded off bank stations and reach lengths
END DESCRIPTION:
XS GIS Cut Line= 6
     3205782.769    13959713.221     3205395.432    13960292.025
     3205198.114    13960633.566       3205207.6    13960825.647
     3205171.793    13961379.706      3205158.39    13961669.064
#Sta/Elev= 30
       0   67.75   12.14   68.12  364.68   65.71  679.26   60.62   877.4   54.51
  956.27   52.53    1054   51.48 1066.24   50.31 1090.89   50.33 1101.45    48.6
 1133.17   47.54  1163.6   46.67 1165.91   46.57 1170.01   45.96 1174.96   47.28
    1180   47.53 1194.02   48.23 1218.43   49.86 1248.45   50.54    1252   52.09
 1258.39   52.36 1353.71    51.5 1450.27   52.37 1486.79   52.99 1718.43   55.17
 1814.85   58.31  1927.7   60.11 1972.79   61.98 2031.21   62.28 2128.09   63.17
#Mann= 3 , 0 , 0
       0     .11       0 1133.17     .06       0    1180     .11       0
#XS Ineff= 2 , 0
       0    1100   52.66    1250       0   52.66
Permanent Ineff=
       F       F
Bank Sta=1133.17,1180
XS Rating Curve= 0
Exp/Cntr=.5,.3

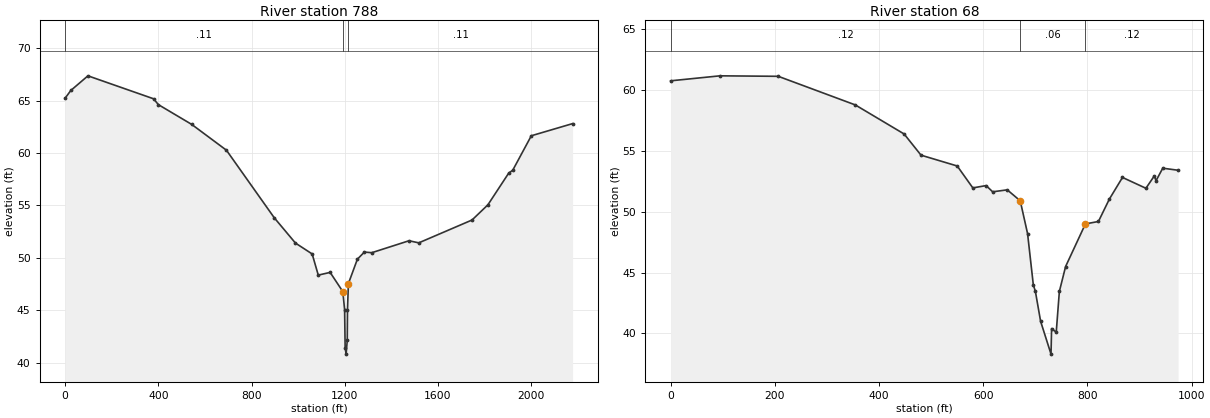
Type RM Length L Ch R = 1 ,788     ,614,720,698
BEGIN DESCRIPTION:
482s1d (1/4 Golf Cart crossing) Lake Houston GC Hole #17
Rounded reach lengths and bank stations
END DESCRIPTION:
XS GIS Cut Line= 6
     3205738.753    13959673.607      3205360.22    13960265.616
      3205150.78    13960628.579     3205159.897    13960696.252
     3205155.689    13960838.612     3205100.483    13961682.689
#Sta/Elev= 30
       0   65.23   24.12   65.96   97.82   67.36   379.4   65.17  400.22   64.61
  543.53   62.72  692.41   60.26  897.82   53.81  988.63    51.4 1060.42   50.36
 1086.64   48.34 1137.58    48.6    1192   46.77 1199.73   45.05 1202.04   41.41
 1206.14    40.8 1211.09   42.12 1212.11   45.05    1216   47.53 1254.56   49.86
 1284.58   50.54 1316.32   50.48 1476.18   51.62  1518.2   51.42 1746.79    53.6
 1814.91   55.05 1904.39   58.08 1921.55   58.35  2001.3   61.64 2178.57    62.8
#Mann= 3 , 0 , 0
       0     .11       0    1192     .06       0    1216     .11       0
Bank Sta=1192,1216
XS Rating Curve= 0
Exp/Cntr=.3,.1

Type RM Length L Ch R = 1 ,68      ,156,68,148
BEGIN DESCRIPTION:
482v3   rounded reach length and bank stations. Both ROB and LOB reach lengths > channel reach length sinceflow lines extended beyond channel centerline as this is the most d/s xsec.
END DESCRIPTION:
XS GIS Cut Line= 6
     3204874.459      13959990.2     3204611.703    13960581.938
     3204526.833     13960682.76     3204506.626    13960713.503
     3204427.098    13960772.639     3204378.158    13960805.266
#Sta/Elev= 30
       0   60.76   94.64   61.17  206.55   61.13  354.37   58.78  448.16   56.39
  480.56   54.65  550.05   53.76  579.99   51.96  605.53   52.15  618.07   51.64
   646.1    51.8     671    50.9   685.1    48.2   696.1      44   700.1   43.45
   710.1      41   730.1    38.3  731.17    40.4   740.1    40.1   746.1   43.45
   758.1    45.5   796.1      49   821.1    49.2  841.95   51.03  867.26   52.82
  912.25   51.93  928.43   52.95  931.66   52.55  944.57   53.58  974.02   53.41
#Mann= 3 , 0 , 0
       0     .12       0     671     .06       0   796.1     .12       0
Bank Sta=671,796.1
XS Rating Curve= 0
Exp/Cntr=.3,.1

Chan Stop Cuts=-1